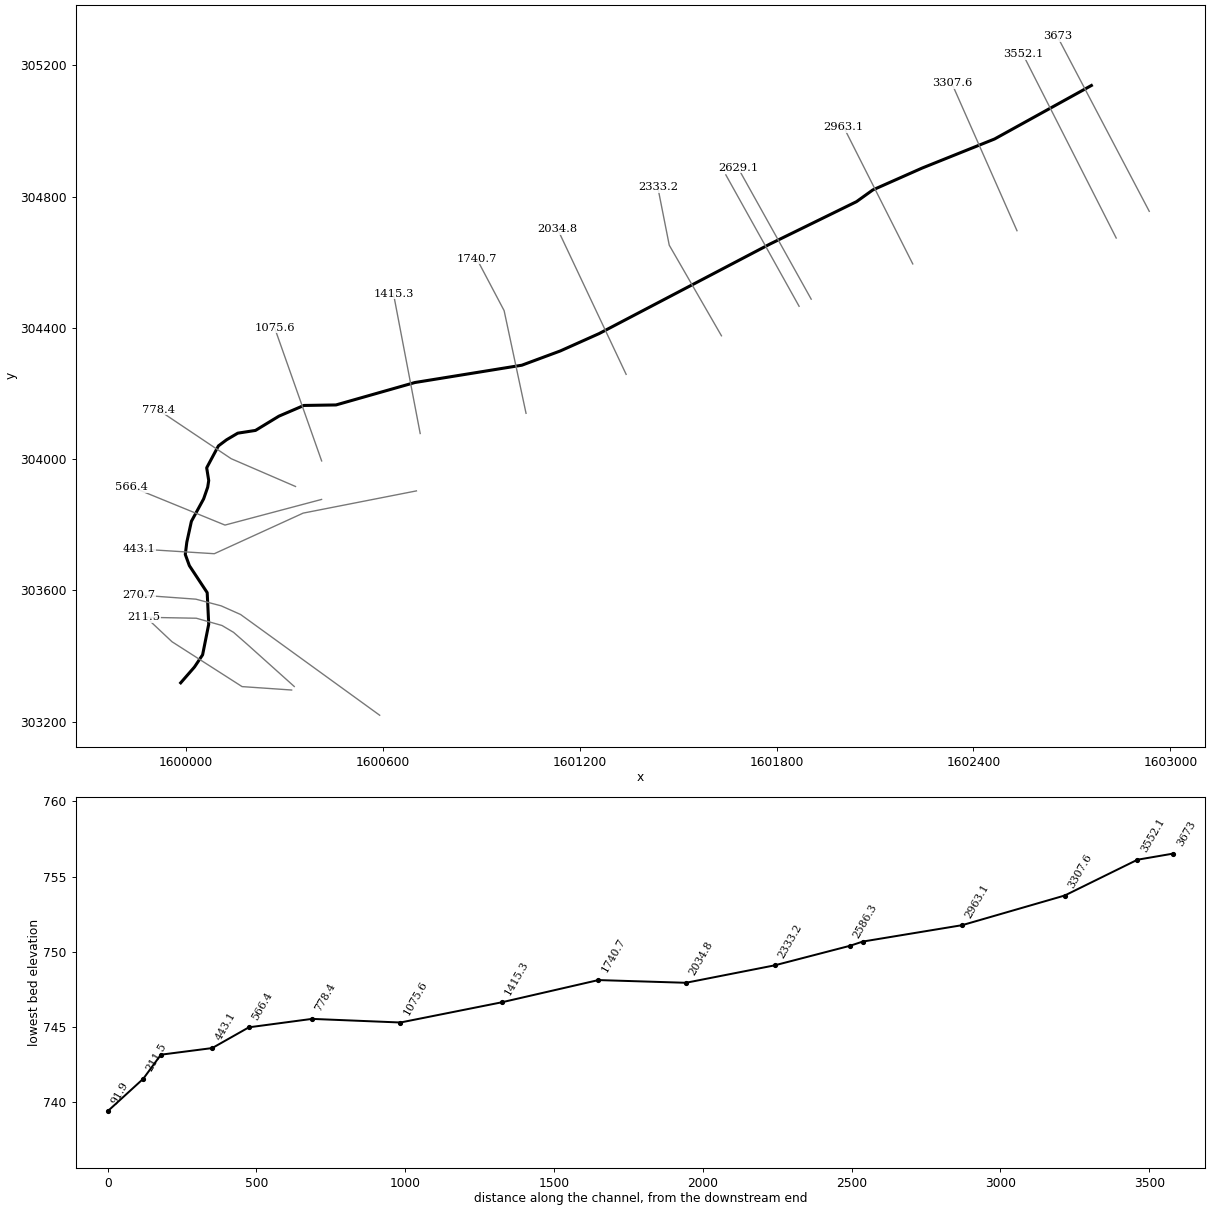
--- NP4.prj (project) ---

Proj Title=NP4
Current Plan=p01
Geom File=g01
Flow File=f01
Plan File=p01
DSS Export Rating Curves=0
DSS Export Rating Curve Sorted=0
DSS Export Volume Flow Curves=0
DXF OffsetX=0
DXF OffsetY=0
DXF ScaleX=0
DXF ScaleY=0

--- NP4.p01 (plan) ---

Plan Title=Floodplain
Program Version=4.00
Geom File=g01
Flow File=f01
K Sum by GR=0
Std Step Tol=0.01
Critical Tol=0.01
Num of Std Step Trials=20
Max Error Tol=0.3
Flow Tol Ratio=0.001
Split Flow NTrial=30
Split Flow Tol=0.02
Split Flow Ratio=0.02
Log Output Level=0
Friction Slope Method=1
Unsteady Friction Slope Method=2
Unsteady Bridges Friction Slope Method=1
Global Log Level=0
CheckData=False
Run HTab=0
Run UNet=0
Run PostProcess=0
UNET Theta=0
UNET Theta Warmup=0
UNET ZTol=0
UNET ZSATol=0
UNET MxIter=0
UNET MaxInSteps=0
UNET DtIC=0
UNET DtMin=0
UNET MaxCRTS=0
UNET WFStab=0
UNET SFStab=0
UNET WFX=0
UNET SFX=0
UNET DSS MLevel=0
UNET DZMax Abort=0
UNET Convert EG Bridges=0
UNET Use Existing IB Tables=0
UNET Froude Limit=0
UNET Froude Power=0
Write IC File=0
Echo Input=False
Echo Output=False
Write Detailed=0

--- NP4.f01 (steady flow) ---

Flow Title=NFF Regression Equation
Program Version=4.10
Number of Profiles= 1
Profile Names=P100yr
River Rch & RM=NP4,Main            ,3673
183.6954
River Rch & RM=NP4,Main            ,2963.1
195.5586
River Rch & RM=NP4,Main            ,2629.1
213.5606
River Rch & RM=NP4,Main            ,1740.7
229.8562
River Rch & RM=NP4,Main            ,566.4
248.8955
River Rch & RM=NP4,Main            ,270.7
349.4495
Boundary for River Rch & Prof#=NP4,Main            , 1
Up Type= 0
Dn Type= 3
Dn Slope=0.0176
DSS Import GetInterval= 0
DSS Import GetPeak= 0
DSS Import FillOption= 0

--- NP4.g01 (geometry) ---

Geom Title=USGS 10m DEM
Program Version=4.10

River Reach=NP4             ,Main
Reach XY= 30
     1602759.429      305138.824     1602464.448      304975.808
      1602243.99      304887.314     1602093.394      304820.556
     1602043.713      304784.847      1601780.56      304655.988
     1601259.221      304382.743     1601141.229      304329.957
     1601024.013      304286.486     1600697.983        304233.7
     1600457.651      304165.389     1600359.842      304163.837
     1600283.768      304131.234     1600212.352      304087.763
     1600158.324      304079.379     1600124.168      304059.196
     1600099.328      304040.566      1600063.62      303973.807
      1600069.83      303934.994     1600066.725      303914.811
     1600054.305      303879.103     1600017.044      303810.792
     1600003.071      303747.138     1599998.414      303709.877
     1600010.834      303675.722     1600065.172      303593.438
      1600069.83      303497.181       1600051.2       303404.03
     1600026.359      303366.769     1599984.441       303318.64

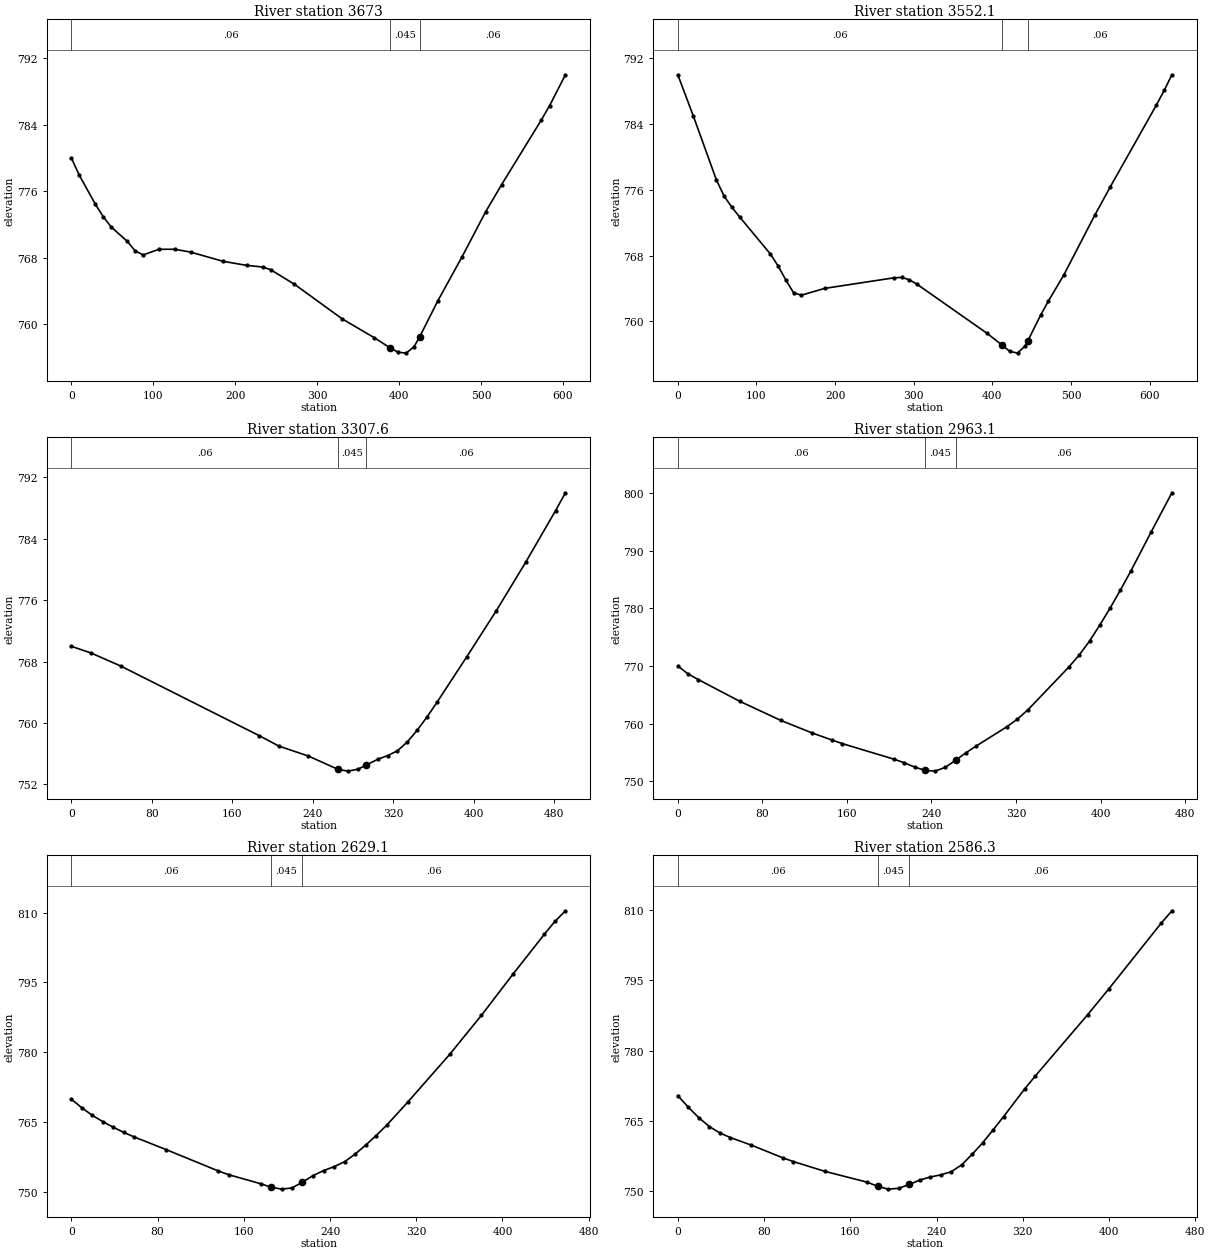
Type RM Length L Ch R = 1 ,3673    ,121.2,120.9,120.6
XS GIS Cut Line= 2
     1602935.721      304755.392     1602655.237      305289.184
#Sta/Elev= 30
       0     780     9.7  777.92    29.2  774.45    38.9  772.94    48.6  771.71
    68.1  769.98    77.8  768.84    87.5  768.34     107  769.02   126.4  769.02
   145.9  768.67   184.8  767.58     214  767.08   233.4  766.89   243.1  766.57
   272.3  764.81   330.7  760.64   369.6  758.39     389  757.16   398.8  756.64
   408.5  756.53   418.2  757.29  424.93758.4625   447.4  762.84   476.6  768.07
   505.7  773.54   525.2  776.81   573.8   784.6   583.6  786.28     603     790
#Mann= 3 , 0 , 0
       0     .06       0     389    .045       0  424.93     .06       0
Bank Sta=389,424.93
XS Rating Curve= 0 ,0
Exp/Cntr=0.3,0.1

Type RM Length L Ch R = 1 ,3552.1  ,245.7,244.5,243.3
XS GIS Cut Line= 2
     1602835.018      304674.035     1602550.538      305234.101
#Sta/Elev= 30
       0  790.01    19.6  785.02    49.1   777.2    58.9  775.23    68.7  773.89
    78.5  772.71   117.8  768.18   127.6  766.72   137.4  765.01   147.2  763.47
     157  763.17   186.5     764   274.8  765.29   284.6  765.34   294.5  765.05
   304.3   764.5   392.6  758.57   412.2  757.11     422  756.34   431.9  756.12
   441.7     757  444.65757.5425   461.3  760.75   471.1  762.45   490.8  765.64
     530  772.89   549.6  776.32   608.5  786.33   618.4  788.11   628.2  790.01
#Mann= 3 , 0 , 0
       0     .06       0   412.2    .045       0  444.65     .06       0
Bank Sta=412.2,444.65
XS Rating Curve= 0 ,0
Exp/Cntr=0.3,0.1

Type RM Length L Ch R = 1 ,3307.6  ,343.4,344.5,345.7
XS GIS Cut Line= 2
     1602532.659      304696.337     1602334.054      305145.471
#Sta/Elev= 22
       0     770    19.6  769.13    49.1  767.43   186.6  758.37   206.3     757
   235.7   755.7   265.2  753.96     275  753.74   284.8  753.99   292.4  754.48
   304.5  755.28   314.3  755.76   324.1  756.39   333.9  757.53   343.8  759.08
   353.6  760.81   363.4   762.7   392.9  768.61   422.3  774.62   451.8     781
   481.3  787.68   491.1     790
#Mann= 3 , 0 , 0
       0     .06       0   265.2    .045       0   292.4     .06       0
Bank Sta=265.2,292.4
XS Rating Curve= 0 ,0
Exp/Cntr=0.3,0.1

Type RM Length L Ch R = 1 ,2963.1  ,333,333.9,334.9
XS GIS Cut Line= 2
     1602215.115      304595.127     1602004.449      305012.483
#Sta/Elev= 29
       0  769.99     9.7  768.61    19.5  767.62    58.4  763.89    97.4  760.56
   126.6  758.42   146.1  757.14   155.8  756.53   204.5  753.84   214.3  753.21
     224  752.48   233.8   751.9   243.5  751.77   253.2  752.44     263  753.67
   272.7  754.96   282.4  756.13   311.7   759.5   321.4   760.8   331.2  762.38
   370.1  769.83   379.8  771.89   389.6  774.31   399.3  777.09   409.1  780.04
   418.8  783.15   428.6  786.42     448  793.26   467.5     800
#Mann= 3 , 0 , 0
       0     .06       0   233.8    .045       0     263     .06       0
Bank Sta=233.8,263
XS Rating Curve= 0 ,0
Exp/Cntr=0.3,0.1

Type RM Length L Ch R = 1 ,2629.1  ,42.8,42.8,42.8
XS GIS Cut Line= 2
     1601905.615      304487.761     1601682.419       304888.12
#Sta/Elev= 30
       0  769.97     9.8   768.1    19.5   766.5    29.3  765.14      39  763.93
    48.8  762.83    58.5  761.85    87.8  759.17   136.5  754.56   146.3  753.75
   175.6  751.84   185.3  751.09     195  750.68   204.8  750.94   213.9  752.11
   224.3  753.59   234.1  754.67   243.8   755.5   253.6  756.57   263.3   758.2
   273.1  760.13   282.8  762.17   292.6   764.4   312.1  769.34   351.1   779.6
   380.4  787.94   409.6  796.74   438.9  805.36   448.6  808.09   458.4  810.37
#Mann= 3 , 0 , 0
       0     .06       0   185.3    .045       0   213.9     .06       0
Bank Sta=185.3,213.9
XS Rating Curve= 0 ,0
Exp/Cntr=0.3,0.1

Type RM Length L Ch R = 1 ,2586.3  ,252.7,253.1,253.4
XS GIS Cut Line= 2
     1601868.722       304466.06     1601645.526      304866.419
#Sta/Elev= 30
       0  770.37     9.8  767.88    19.5  765.65    29.3  763.76      39   762.4
    48.8  761.41    68.3  759.79    97.5  757.08   107.3  756.28   136.5  754.19
   175.6  751.89   185.3  751.02     195   750.4   204.8  750.57   214.6  751.39
   224.3  752.32   234.1  752.98   243.8  753.44   253.6  754.11   263.3  755.58
   273.1  757.84   282.8  760.29   292.6  763.08   302.3  765.91   321.8   771.8
   331.6  774.55   380.4   787.7   399.9  793.18   448.6  807.25   458.4  809.85
#Mann= 3 , 0 , 0
       0     .06       0   185.3    .045       0   214.6     .06       0
Bank Sta=185.3,214.6
XS Rating Curve= 0 ,0
Exp/Cntr=0.3,0.1

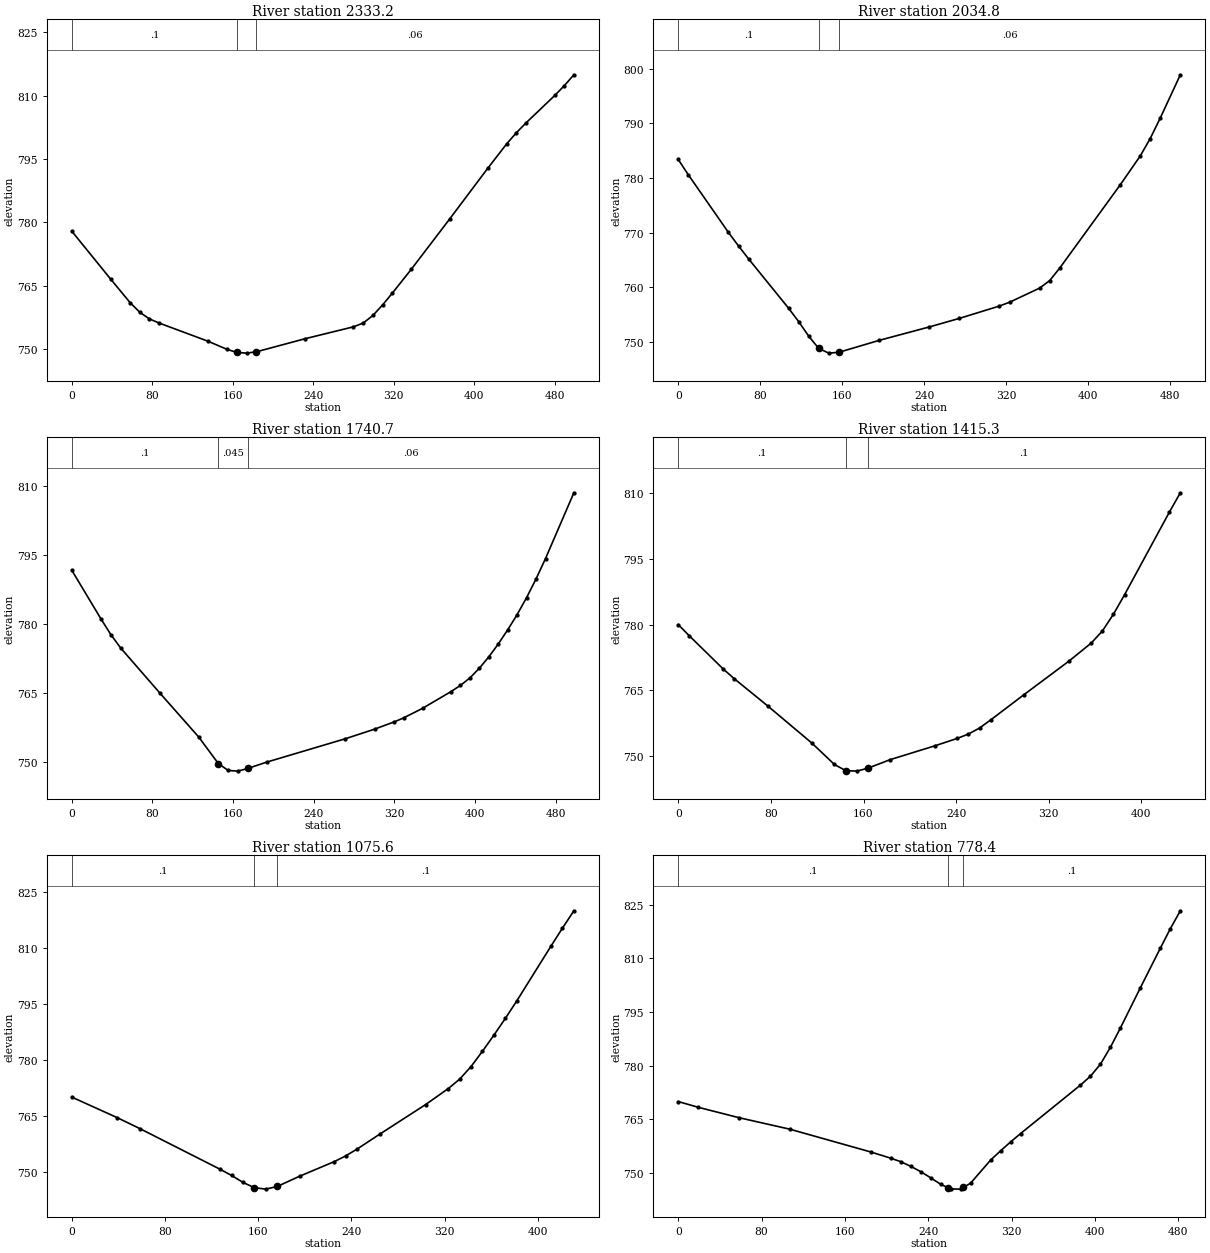
Type RM Length L Ch R = 1 ,2333.2  ,300.3,298.4,296.6
XS GIS Cut Line= 3
      1601632.16      304376.109     1601473.117      304652.094
     1601438.137      304829.031
#Sta/Elev= 26
       0  777.95    38.6  766.62    57.9  761.06    67.6  758.76    77.2  757.19
    86.9  756.21   135.1  751.94   154.4  749.98   164.1  749.26   173.7   749.1
   183.4  749.41   231.7   752.5   279.9  755.32   289.6  756.21   299.2  758.01
   308.9  760.51   318.5  763.28   337.5  768.97   375.5  780.83   413.5  792.87
   432.4  798.68   441.9  801.25   451.4  803.56   479.9  810.04   489.4  812.36
   498.9  814.93
#Mann= 3 , 0 , 0
       0      .1       0   164.1    .045       0   183.4     .06       0
Bank Sta=164.1,183.4
XS Rating Curve= 0 ,0
Exp/Cntr=0.3,0.1

Type RM Length L Ch R = 1 ,2034.8  ,299.3,294.1,288.9
XS GIS Cut Line= 2
     1601341.718      304258.624     1601132.683      304701.532
#Sta/Elev= 24
       0  783.37     9.8  780.58      49  770.02    58.8  767.55    68.6  765.19
   107.8  756.12   117.5   753.7   127.3  751.04   137.1  748.79   146.9  747.94
   156.7  748.09   195.9  750.27   244.9  752.73   274.3   754.3   313.4  756.56
   323.2  757.25   352.6  759.84   362.4  761.22   372.2  763.51     431  778.68
   450.6  783.98   460.4  787.19   470.2  790.94   489.8  798.86
#Mann= 3 , 0 , 0
       0      .1       0   137.1    .045       0   156.7     .06       0
Bank Sta=137.1,156.7
XS Rating Curve= 0 ,0
Exp/Cntr=0.3,0.1

Type RM Length L Ch R = 1 ,1740.7  ,325.9,325.4,324.9
XS GIS Cut Line= 3
     1601036.715      304139.929     1600969.941      304452.763
     1600886.769      304610.372
#Sta/Elev= 28
       0  791.79    29.1  781.16    38.8  777.79    48.5  774.89    87.2  765.14
     126  755.52   145.4  749.77   155.1  748.27   164.8  748.12   174.5   748.7
   193.9  750.11   271.4  755.16   300.5  757.25   319.9  758.83   329.3   759.7
     348  761.77   376.2  765.41   385.5  766.74   394.9  768.36   404.3  770.48
   413.7  772.95     423  775.72   432.4  778.81   441.8  782.14   451.2  785.83
   460.6   789.9     470  794.34   498.1  808.62
#Mann= 3 , 0 , 0
       0      .1       0   145.4    .045       0   174.5     .06       0
Bank Sta=145.4,174.5
XS Rating Curve= 0 ,0
Exp/Cntr=0.3,0.1

Type RM Length L Ch R = 1 ,1415.3  ,336.2,339.7,343.2
XS GIS Cut Line= 2
     1600714.201      304078.349     1600632.755      304504.279
#Sta/Elev= 24
       0     780     9.6  777.44    38.6  769.96    48.2  767.72    77.1  761.52
   115.6  752.98   134.9  748.15   144.6  746.76   154.2  746.64   163.8  747.31
   183.1  749.26   221.6   752.4   240.9  754.08   250.6  755.08   260.2  756.45
   269.8  758.29   298.7  764.07   337.3  771.66   356.6  775.78   366.2   778.5
   375.8  782.34   385.5  786.82     424  805.53   433.6     810
#Mann= 3 , 0 , 0
       0      .1       0   144.6    .045       0   163.8      .1       0
Bank Sta=144.6,163.8
XS Rating Curve= 0 ,0
Exp/Cntr=0.3,0.1

Type RM Length L Ch R = 1 ,1075.6  ,282.4,297.2,311.8
XS GIS Cut Line= 2
     1600413.896        303994.8      1600270.39      304401.065
#Sta/Elev= 25
       0     770    39.2  764.46    58.8  761.49   127.3  750.63   137.1  748.98
   146.9  747.11   156.7  745.69   166.5   745.3   176.3  746.01   195.8   748.8
   225.2  752.67     235   754.2   244.8  756.04   264.4  760.07   303.6  767.98
   323.2  772.31   332.9  774.82   342.7  778.21   352.5  782.32   362.3  786.63
   372.1  791.12   381.9  795.81   411.3  810.54   421.1  815.34   430.9     820
#Mann= 3 , 0 , 0
       0      .1       0   156.7    .045       0   176.3      .1       0
Bank Sta=156.7,176.3
XS Rating Curve= 0 ,0
Exp/Cntr=0.3,0.1

Type RM Length L Ch R = 1 ,778.4   ,207,212,217.1
XS GIS Cut Line= 3
     1600334.262      303916.955      1600138.19      304001.648
     1599915.391      304150.897
#Sta/Elev= 29
       0     770    19.4  768.38    58.2   765.5   106.8   762.3   184.5  755.94
   203.9  754.18   213.6   753.2   223.2   751.9   232.7  750.41   242.3   748.7
   251.9  746.88   258.7  745.97   261.5  745.59     271  745.54   273.7  746.01
   280.6  747.22   299.8  753.66   309.4  756.26   318.9  758.71   328.5  761.06
     386   774.6   395.6  777.09   405.1  780.42   414.7  785.14   424.3  790.54
   443.4  801.74   462.6  812.82   472.2  818.26   481.8  823.27
#Mann= 3 , 0 , 0
       0      .1       0   258.7    .045       0   273.7      .1       0
Bank Sta=258.7,273.7
XS Rating Curve= 0 ,0
Exp/Cntr=0.3,0.1

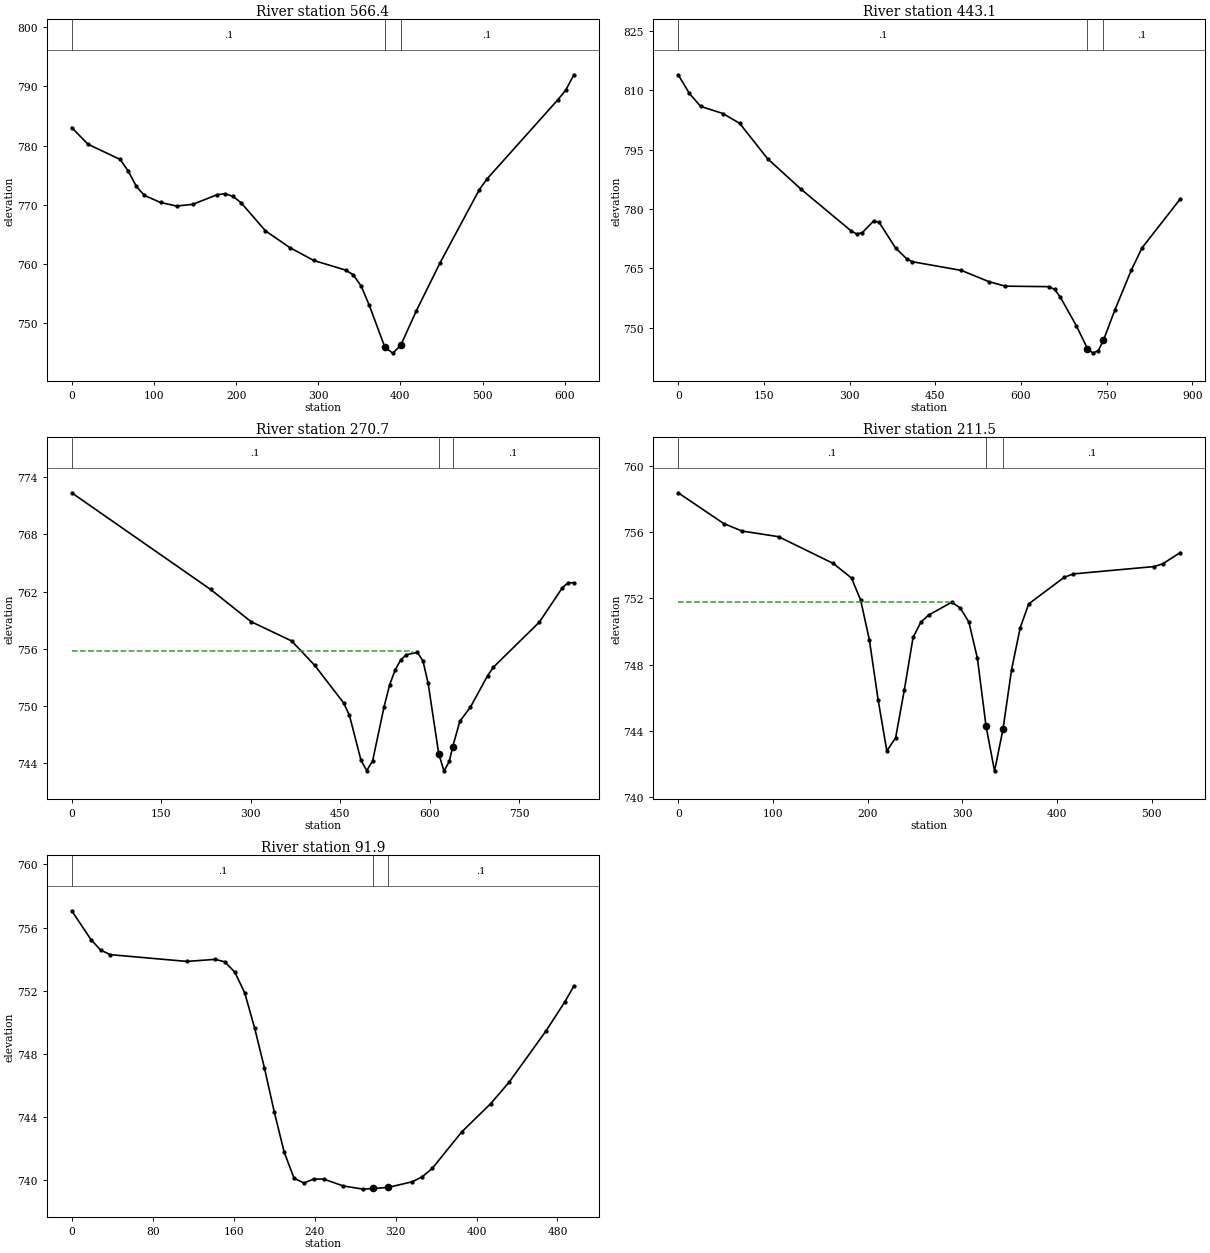
Type RM Length L Ch R = 1 ,566.4   ,115.9,123.3,130.6
XS GIS Cut Line= 3
     1600413.654      303877.459     1600119.384      303799.334
     1599835.529       303915.22
#Sta/Elev= 30
       0  783.04    19.6  780.24    58.9  777.66    68.8  775.68    78.6  773.11
    88.4   771.6     108   770.4   127.7   769.8   147.3  770.09   176.8   771.7
   186.6  771.89   196.4  771.41   206.2  770.34   235.7  765.62   265.2   762.8
   294.6  760.61   333.2     759   342.8  758.18   352.4  756.25     362  753.09
   381.1  745.97   390.7  744.98   400.3  746.27   419.4  752.12   448.2   760.2
   496.1  772.58   505.7  774.42   591.9  787.77   601.5  789.42   611.1  791.94
#Mann= 3 , 0 , 0
       0      .1       0   381.1    .045       0   400.3      .1       0
Bank Sta=381.1,400.3
XS Rating Curve= 0 ,0
Exp/Cntr=0.3,0.1

Type RM Length L Ch R = 1 ,443.1   ,177.1,172.4,167.4
XS GIS Cut Line= 4
     1600702.717      303903.501     1600357.665      303835.793
     1600086.832      303712.095     1599857.665      303726.418
#Sta/Elev= 30
       0  813.95    19.5  809.26    39.1  805.98    78.1  804.17   107.4  801.71
   156.3  792.77   214.9  785.05   302.8  774.48   312.6  773.73   322.3  774.07
   341.9  776.97   351.6  776.68   380.4  770.19   399.7  767.48   409.3  766.72
   495.7  764.51   543.7  761.68   572.5  760.53   649.4   760.4   658.9   759.7
   668.5  757.86   697.2  750.46   716.4  744.76   725.9   743.6   735.5  744.26
   744.5  746.89   764.2  754.42   792.9  764.49     812  770.21     879  782.59
#Mann= 3 , 0 , 0
       0      .1       0   716.4    .045       0   744.5      .1       0
Bank Sta=716.4,744.5
XS Rating Curve= 0 ,0
Exp/Cntr=0.3,0.1

Type RM Length L Ch R = 1 ,270.7   ,59.7,59.2,58.8
XS GIS Cut Line= 5
     1600590.738      303219.907     1600166.896      303526.879
     1600107.665      303553.241     1600030.616      303573.575
     1599857.795      303586.154
#Sta/Elev= 30
       0  772.36   232.6  762.22   300.4  758.84   368.3  756.82     407  754.26
   455.5  750.31   465.2     749   484.6  744.28   494.2  743.22     504  744.24
   523.3  749.94   532.6  752.23   541.8  753.78   551.1  754.83   560.4  755.37
   578.9  755.62   588.2  754.75     597  752.38   614.7     745   623.6  743.16
   632.4  744.18     638  745.68   650.1  748.39   667.8  749.87   696.7  753.18
   706.4  754.07   783.4   758.8   821.9   762.4   831.5  762.93   841.1  762.92
#Mann= 3 , 0 , 0
       0      .1       0   614.7    .045       0     638      .1       0
#XS Ineff= 2 , 0
          570.42  755.72
Permanent Ineff=
       F       F
Bank Sta=614.7,638
XS Rating Curve= 0 ,0
Exp/Cntr=0.3,0.1

Type RM Length L Ch R = 1 ,211.5   ,126.1,119.7,113.2
XS GIS Cut Line= 6
     1600330.451      303307.509     1600187.092      303436.053
     1600145.425      303472.511     1600110.269      303493.345
     1600032.144       303515.48     1599872.118      303518.446
#Sta/Elev= 30
       0  758.38    48.1  756.52    67.4  756.07   105.9  755.73   163.7  754.11
   182.9  753.23   192.6  751.89   201.8  749.48     211  745.87   220.2  742.78
   229.5  743.58   238.7  746.48   247.9  749.64   256.1  750.56   264.3  750.99
   288.8  751.77   297.8  751.41   306.8  750.57   315.8  748.38   324.9  744.29
   333.9  741.56   342.9  744.12   351.9   747.7     361  750.23     370  751.67
   407.6  753.28   417.1  753.48   501.8  753.92   511.2  754.08     530  754.77
#Mann= 3 , 0 , 0
       0      .1       0   324.9    .045       0   342.9      .1       0
#XS Ineff= 2 , 0
          289.86  751.76
Permanent Ineff=
       F       F
Bank Sta=324.9,342.9
XS Rating Curve= 0 ,0
Exp/Cntr=0.3,0.1

Type RM Length L Ch R = 1 ,91.9    ,95.2,91.9,88.5
XS GIS Cut Line= 4
     1600322.509       303296.73     1600171.467      303307.147
     1599957.925      303443.866     1599891.519      303506.366
#Sta/Elev= 30
       0  757.06    18.9  755.24    28.4  754.58    37.8  754.28   113.6  753.85
   141.9  753.98   151.4  753.82   161.2  753.16   170.9  751.86   180.7  749.63
   190.4  747.09   200.2  744.28   209.9  741.75   219.7  740.09   229.4  739.79
   239.2  740.04   248.9  740.04   268.4   739.6   287.9   739.4   297.7  739.44
   312.7  739.51   336.7  739.87   346.4  740.19   356.2  740.71   385.4  743.03
   414.1  744.83   432.3  746.19   468.8  749.45     487  751.25   496.2  752.28
#Mann= 3 , 0 , 0
       0      .1       0   297.7    .045       0   312.7      .1       0
Bank Sta=297.7,312.7
XS Rating Curve= 0 ,0
Exp/Cntr=0.3,0.1

Chan Stop Cuts=-1
Use User Specified Reach Order=0
Composite Channel Slope=5